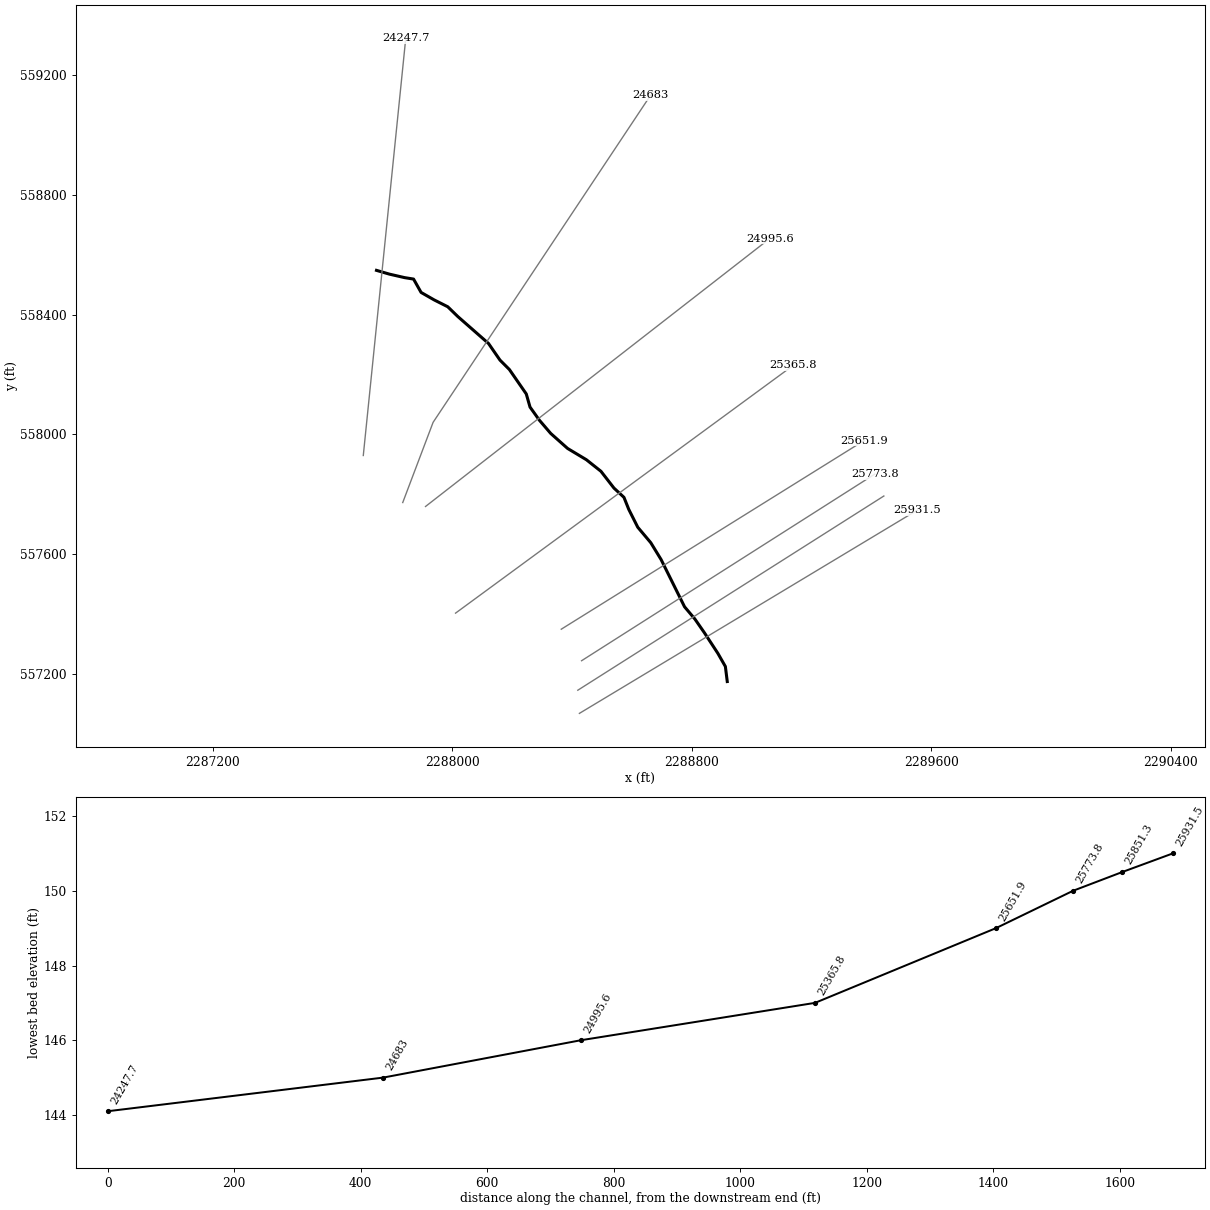
--- Yellow Marsh Branch.prj (project) ---

Proj Title=Yellow Marsh Branch
Current Plan=p01
Default Exp/Contr=0,0
English Units
Geom File=g01
Flow File=f01
Flow File=f02
Plan File=p01
Plan File=p02
BEGIN DESCRIPTION:
END DESCRIPTION:
DSS Export Rating Curves= 0
DSS Export Rating Curve Sorted= 0
DSS Export Volume Flow Curves= 0
DXF OffsetX= 0
DXF OffsetY= 0
DXF ScaleX= 0
DXF ScaleY= 0

--- Yellow Marsh Branch.p01 (plan) ---

Plan Title=Existing Conditions
Program Version=4.00
Short Identifier=Ex
Geom File=g01
Flow File=f01
Subcritical Flow
K Sum by GR= 0
Std Step Tol= 0.01
Critical Tol= 0.01
Num of Std Step Trials= 20
Max Error Tol= 0.3
Flow Tol Ratio= 0.001
Split Flow NTrial= 30
Split Flow Tol= 0.02
Split Flow Ratio= 0.02
Log Output Level= 0
Friction Slope Method= 1
Unsteady Friction Slope Method= 2
Unsteady Bridges Friction Slope Method= 1
Parabolic Critical Depth
Global Vel Dist= 0 , 0 , 0
Global Log Level= 0
CheckData=True
Encroach Param=-1 ,0,0, 2
Encroach River=Yellow Marsh ...
Encroach Reach=Main
Encroach Node=25931.5
       1    9963   10011
Encroach Node=25851.3
       1    9970   10010
Encroach Node=25773.8
       1    9982   10020
Encroach Node=25651.9
       1    9965   10040
Encroach Node=25365.8
       1    9923   10074
Encroach Node=24995.6
       1    9938   10090
Encroach Node=24683
       1    9940 10076.8
Encroach Node=24247.7
       1    9980   10025
Run HTab= 0
Run UNet= 0
Run PostProcess= 0
Run WQNet= 0
UNET Theta= 0
UNET Theta Warmup= 0
UNET ZTol= 0
UNET ZSATol= 0
UNET MxIter= 0
UNET MaxInSteps= 0
UNET DtIC= 0
UNET DtMin= 0
UNET MaxCRTS= 0
UNET WFStab= 0
UNET SFStab= 0
UNET WFX= 1
UNET SFX= 1
UNET DSS MLevel= 1
UNET DZMax Abort= 0
UNET Convert EG Bridges= 0
UNET Use Existing IB Tables= 0
UNET Froude Reduction=False
UNET Froude Limit= 0
UNET Froude Power= 0
UNET Time Slicing=0,0, 5
Write IC File= 0
Echo Input=False
Echo Output=False
Write Detailed= 0
Detailed Automatic Start=False, 0
WQ ULTIMATE=-1
WQ Max Comp Step=1HOUR
WQ Output Interval=15MIN
WQ Output Selected Increments= 0
WQ Output face flow=0
WQ Output face velocity=0
WQ Output face area=0
WQ Output face dispersion=0
WQ Output cell volume=0
WQ Output cell surface area=0
WQ Output cell continuity=0
WQ Output face conc=0
WQ Output face dconc_dx=0
WQ Output face courant=0
WQ Output face peclet=0
WQ Output face adv mass=0
WQ Output face disp mass=0
WQ Output cell mass=0
WQ Output cell source sink temp=0
WQ Output cell source sink nsm=0
WQ Output MaxMinRange=-1
WQ Daily Max Min Mean=-1
WQ Daily Range=0
WQ Daily Time=0
WQ Create Restart=0
WQ Fixed Restart=0
WQ System Summary=False
Sorting and Armoring Iterations= 10
XS Update Threshold= 0.02
Hydraulics Update Threshold= 0.02
Energy Slope Method= 1
Volume Change Method= 0
XS Weighting Method= 0
Number of US Weighted Cross Sections= 1
Number of DS Weighted Cross Sections= 1
Upstream XS Weight=0.25
Main XS Weight=0.5
Downstream XS Weight=0.25
Number of DS XS's Weighted with US Boundary= 1
Upstream Boundary Weight= 1
Weight of XSs Associated with US Boundary= 0
Number of US XS's Weighted with DS Boundary= 1
Downstream Boundary Weight= 0.5
Weight of XSs Associated with DS Boundary= 0.5
Sediment Output Level= 4
Mass or Volume Output= 0
Output Increment Type= 1
Profile and TS Output Increment= 10
XS Output Flag= 0
XS Output Increment= 10
Disregard all LS=0
Disregard all Conn=0
Disregard all Breaches=0
Disregard all Pumps=0

--- Yellow Marsh Branch.p02 (plan) ---

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Plan Title=Future Conditions
Short Identifier=Fut
Geom File=g01
Flow File=f02
Encroach Param=-1 ,0,0, 0
Computation Interval=1HOUR
Output Interval=1HOUR
UNET Theta= 1
UNET Theta Warmup= 1
UNET ZTol= 0.02
UNET ZSATol= 0.05
UNET MxIter= 20
UNET MaxCRTS= 20
UNET WFStab= 2
UNET SFStab= 1
UNET DSS MLevel= 4
UNET DZMax Abort= 100
UNET Use Existing IB Tables=-1
UNET Froude Limit= 1
UNET Froude Power= 10
Instantaneous Interval=1HOUR
Detailed Automatic Start=False, 10

--- Yellow Marsh Branch.f01 (steady flow) ---

Flow Title=USGS Regression 10, 25, 50, 100, 500
Program Version=4.00
Number of Profiles= 6
Profile Names=P100yr,FWY,P10yr,P25yr,P50yr,P500yr
River Rch & RM=Yellow Marsh ...,Main            ,25931.5
     537     537     249     349     438     772
Boundary for River Rch & Prof#=Yellow Marsh ...,Main            , 1
Up Type= 0
Dn Type= 1
Dn Known WS=154.59
Boundary for River Rch & Prof#=Yellow Marsh ...,Main            , 2
Up Type= 0
Dn Type= 1
Dn Known WS=155.43
Boundary for River Rch & Prof#=Yellow Marsh ...,Main            , 3
Up Type= 0
Dn Type= 1
Dn Known WS=151.65
Boundary for River Rch & Prof#=Yellow Marsh ...,Main            , 4
Up Type= 0
Dn Type= 1
Dn Known WS=153.44
Boundary for River Rch & Prof#=Yellow Marsh ...,Main            , 5
Up Type= 0
Dn Type= 1
Dn Known WS=154.02
Boundary for River Rch & Prof#=Yellow Marsh ...,Main            , 6
Up Type= 0
Dn Type= 1
Dn Known WS=158.21
DSS Import GetInterval= 0
DSS Import GetPeak= 0
DSS Import FillOption= 0

--- Yellow Marsh Branch.f02 (steady flow) ---

Flow Title=USGS Regression 100-10%,100-20%,100-35%
Program Version=4.00
Number of Profiles= 3
Profile Names=FC10,FC20,FC35
River Rch & RM=Yellow Marsh ...,Main            ,25931.5
    1140    1460    1780
Boundary for River Rch & Prof#=Yellow Marsh ...,Main            , 1
Up Type= 0
Dn Type= 1
Dn Known WS=166.67
Boundary for River Rch & Prof#=Yellow Marsh ...,Main            , 2
Up Type= 0
Dn Type= 1
Dn Known WS=167.12
Boundary for River Rch & Prof#=Yellow Marsh ...,Main            , 3
Up Type= 0
Dn Type= 1
Dn Known WS=167.22
DSS Import GetInterval= 0
DSS Import GetPeak= 0
DSS Import FillOption= 0

--- Yellow Marsh Branch.g01 (geometry) ---

Geom Title=Detailed Survey and LiDAR Data
Program Version=4.00

River Reach=Yellow Marsh ...,Main
Reach XY= 30
     2288918.458      557175.411     2288912.182      557225.604
     2288887.088      557269.521     2288842.063      557338.309
     2288810.324      557384.036     2288775.834      557424.862
     2288697.411      557582.664     2288662.974       557638.85
     2288619.558      557690.376     2288589.501      557750.012
     2288573.391      557790.255     2288540.052      557821.094
      2288496.54      557877.167     2288447.917      557915.729
     2288385.177      557953.375     2288328.714      558003.563
     2288291.068      558047.484     2288259.698      558091.401
     2288247.151      558135.318     2288190.687       558216.88
     2288159.318      558248.245     2288120.985      558303.783
     2288018.455      558393.679     2287984.926      558426.236
     2287939.729       558449.01     2287895.812      558474.109
     2287870.681      558518.689     2287840.715      558523.536
     2287789.816      558535.214     2287746.851      558547.773

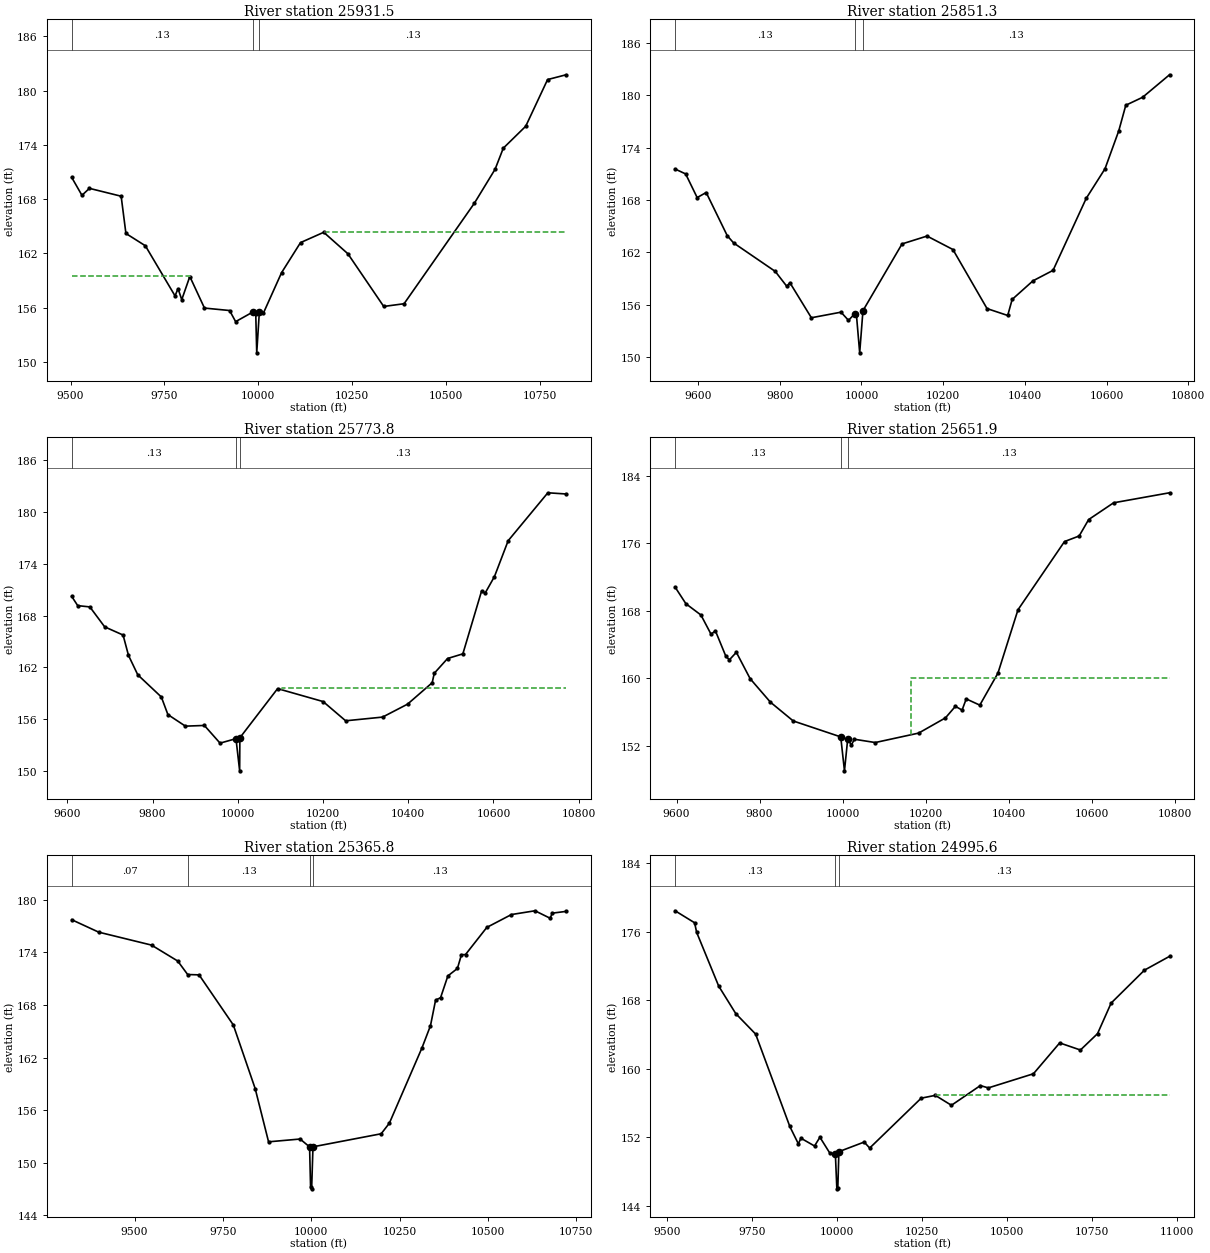
Type RM Length L Ch R = 1 ,25931.5 ,79.3,80.2,82.3
XS GIS Cut Line= 2
     2288424.626      557069.165     2289553.191      557747.468
#Sta/Elev= 30
    9503   170.4  9530.3  168.42  9550.2  169.19  9634.7  168.32  9647.4   164.2
  9699.2  162.84  9778.2   157.3  9786.2   158.1  9796.1  156.88  9817.6  159.44
  9856.6  155.95  9923.5  155.68  9939.6  154.45  9985.7  155.52  9993.2  155.29
  9995.8     151 10002.8  155.55 10013.4  155.38   10062  159.87 10112.4  163.19
 10174.2  164.33 10238.5  161.96   10334  156.13 10388.2  156.43 10575.5  167.55
 10630.7  171.31 10652.4  173.63 10712.2  176.06 10770.4  181.22 10819.7  181.75
#Mann= 3 ,-1 , 0
    9503     .13       0  9985.7    .048       0 10002.8     .13       0
#XS Ineff= 2 , 0
         9817.65  159.5110174.19          164.36
Permanent Ineff=
       F       F
Bank Sta=9985.7,10002.8
XS Rating Curve= 0 ,0
Exp/Cntr=0.3,0.1

Type RM Length L Ch R = 1 ,25851.3 ,76.9,77.5,77.2
XS GIS Cut Line= 2
     2288419.314      557146.468     2289441.545       557794.67
#Sta/Elev= 30
  9543.8  171.56  9569.6     171  9597.8  168.29  9619.9  168.87  9671.5  163.92
  9687.1  163.09    9789  159.83  9817.1  158.13  9824.9  158.53  9877.4  154.52
    9950  155.16  9968.3  154.22  9983.5  154.98  9987.8  154.82  9995.7   150.5
 10003.7  155.33 10099.4  162.98 10160.6  163.88 10223.9  162.34 10307.5  155.57
 10358.1  154.78   10369  156.62 10419.9  158.75 10469.1  159.95 10550.3   168.2
 10596.3  171.59   10630  175.94 10647.2  178.87 10688.3  179.78 10754.2  182.36
#Mann= 3 ,-1 , 0
  9543.8     .13       0  9983.5    .048       0 10003.7     .13       0
#XS Ineff= 2 , 0
       0                 10160.6       0  163.88
Permanent Ineff=
       F       F
Bank Sta=9983.5,10003.7
XS Rating Curve= 0 ,0
Exp/Cntr=0.3,0.1

Type RM Length L Ch R = 1 ,25773.8 ,122,121.9,121.9
XS GIS Cut Line= 2
     2288431.879      557244.869     2289411.001      557867.638
#Sta/Elev= 30
  9610.1  170.22  9624.2  169.15  9652.7     169  9687.5  166.69  9730.7  165.74
  9743.4  163.38  9765.2  161.13  9820.5  158.56  9835.9  156.52    9877  155.18
  9921.5  155.26  9958.3  153.21  9995.7  153.73 10004.3     150 10004.8  153.83
 10093.4  159.53 10200.2  158.03 10253.1   155.8 10339.8  156.23 10398.4  157.73
 10456.2  160.21 10461.1  161.31 10492.3  163.02 10528.2  163.56   10572  170.82
 10580.6  170.61 10602.4  172.52 10634.5  176.67 10727.7  182.23 10770.5  182.09
#Mann= 3 ,-1 , 0
  9610.1     .13       0  9995.7    .048       0 10004.8     .13       0
#XS Ineff= 2 , 0
       0                 10103.4       0  159.56
Permanent Ineff=
       F       F
Bank Sta=9995.7,10004.8
XS Rating Curve= 0 ,0
Exp/Cntr=0.3,0.1

Type RM Length L Ch R = 1 ,25651.9 ,279.2,286.1,287.2
XS GIS Cut Line= 2
     2288364.003      557350.078     2289375.366      557979.634
#Sta/Elev= 30
  9596.4  170.81  9622.4  168.84  9658.6   167.5  9682.9  165.23  9693.6  165.61
  9718.7   162.6  9727.2  162.18    9744  163.07  9777.2  159.94  9826.1  157.15
  9881.1  154.92  9995.5  153.03 10004.5     149 10012.4  152.83 10020.9  152.04
 10028.4  152.75 10078.7  152.36 10183.2  153.48 10247.9  155.29 10271.8  156.66
 10287.9  156.21 10297.9  157.54 10330.6   156.8 10374.3   160.6 10422.6  168.12
 10534.7  176.22   10570  176.88 10592.9  178.83   10653  180.82 10787.7  182.01
#Mann= 3 ,-1 , 0
  9596.4     .13       0  9995.5    .048       0 10012.4     .13       0
#XS Ineff= 2 , 0
       0                   10165       0     160
Permanent Ineff=
       F       F
Bank Sta=9995.5,10012.4
XS Rating Curve= 0 ,0
Exp/Cntr=0.3,0.1

Type RM Length L Ch R = 1 ,25365.8 ,361.1,370.2,364.6
XS GIS Cut Line= 2
     2288010.952      557403.735     2289139.494      558231.129
#Sta/Elev= 30
  9321.9  177.74  9398.2  176.32  9547.8  174.84    9622  173.02  9650.1  171.48
  9682.4  171.44  9779.3  165.72  9841.2  158.45  9879.1  152.37  9968.4  152.69
  9995.2  151.79    9998   147.2   10001     147 10004.8   151.8 10197.8  153.29
   10221   154.5 10313.6  163.13 10337.4  165.64 10351.8  168.55   10366  168.84
 10386.6  171.32 10413.6  172.17   10425  173.74 10436.5  173.76 10496.8  176.86
 10566.5  178.33 10633.2  178.76 10675.9  177.91 10682.3  178.49 10721.2  178.69
#Mann= 4 ,-1 , 0
  9321.9     .07       0  9650.1     .13       0  9995.2    .048       0
 10004.8     .13       0
Bank Sta=9995.2,10004.8
XS Rating Curve= 0 ,0
Exp/Cntr=0.3,0.1

Type RM Length L Ch R = 1 ,24995.6 ,285.9,312.6,335.2
XS GIS Cut Line= 2
      2287910.57      557759.636     2289060.404      558653.952
#Sta/Elev= 30
  9522.7  178.45  9580.1  177.05  9586.2  175.93  9651.1  169.66  9701.4  166.45
  9759.9  164.06  9860.6  153.28  9885.8  151.25  9893.3  151.91  9933.4     151
  9949.3  152.02  9978.8  150.15  9994.8  150.08  9999.2     146   10002   146.1
 10005.2  150.34 10079.7  151.46 10095.9  150.76 10247.6  156.58 10289.2  156.91
 10336.7  155.75 10421.9  158.05 10445.4  157.78 10578.3  159.43 10655.6  163.03
 10716.7   162.2 10767.1  164.11 10807.2  167.68 10905.3  171.52 10979.1  173.13
#Mann= 3 ,-1 , 0
  9522.7     .13       0  9994.8    .048       0 10005.2     .13       0
#XS Ineff= 2 , 0
                        10289.17          156.91
Permanent Ineff=
       F       F
Bank Sta=9994.8,10005.2
XS Rating Curve= 0 ,0
Exp/Cntr=0.3,0.1

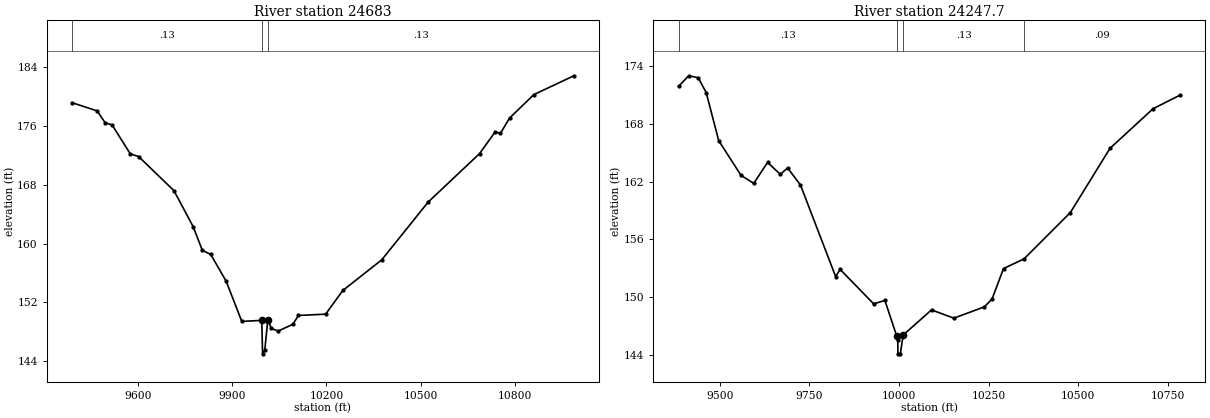
Type RM Length L Ch R = 1 ,24683   ,414.4,435.3,449.8
XS GIS Cut Line= 3
     2287834.523      557772.817     2287935.919      558040.504
     2288661.917      559131.529
#Sta/Elev= 30
  9390.8  179.17  9470.6  178.05  9496.2  176.43  9518.3  176.14  9575.9  172.22
  9602.6  171.84  9714.8  167.21  9776.2   162.3  9805.2  159.09  9832.1  158.52
    9881  154.89  9930.9  149.41  9994.5  149.55    9997     145   10004   145.5
 10013.8  149.66 10024.6  148.46 10046.8   148.1 10093.3  149.02 10111.2  150.22
 10197.6   150.4 10252.4  153.62 10376.5   157.8 10523.8  165.64 10687.6  172.25
 10737.4  175.21 10753.7  174.98 10782.9  177.07 10859.9  180.26 10987.6  182.83
#Mann= 3 ,-1 , 0
  9390.8     .13       0  9994.5    .048       0 10013.8     .13       0
Bank Sta=9994.5,10013.8
XS Rating Curve= 0 ,0
Exp/Cntr=0.3,0.1

Type RM Length L Ch R = 1 ,24247.7 ,24247.7,24247.7,24247.7
XS GIS Cut Line= 2
     2287702.745      557929.849     2287844.583      559322.182
#Sta/Elev= 30
    9385  171.91  9413.4  173.02  9439.8  172.82  9462.1  171.28    9497  166.28
  9559.3  162.66  9594.8  161.83  9633.3  164.01  9668.8  162.77  9689.3  163.43
  9725.1  161.66  9823.1  152.14  9835.8  152.88  9929.2   149.3  9960.6  149.65
  9993.5  145.95  9996.4  145.59  9996.8   144.1 10003.6  144.12 10011.6  146.06
 10090.6  148.67 10152.9  147.81 10238.1  148.99 10259.5  149.81 10291.4  152.97
 10348.4  153.97 10477.9   158.8 10588.5  165.48 10708.7   169.6 10784.5  171.02
#Mann= 4 ,-1 , 0
    9385     .13       0  9993.5    .048       0 10011.6     .13       0
 10348.4     .09       0
Bank Sta=9993.5,10011.6
XS Rating Curve= 0 ,0
Exp/Cntr=0.5,0.3
Stream Node=Yellow Marsh ...,Main            , 0 , 0 ,Upstream end
Stream Node=Yellow Marsh ...,Main            , 0 , 1 ,Downstream end

Chan Stop Cuts=-1
Use User Specified Reach Order=0